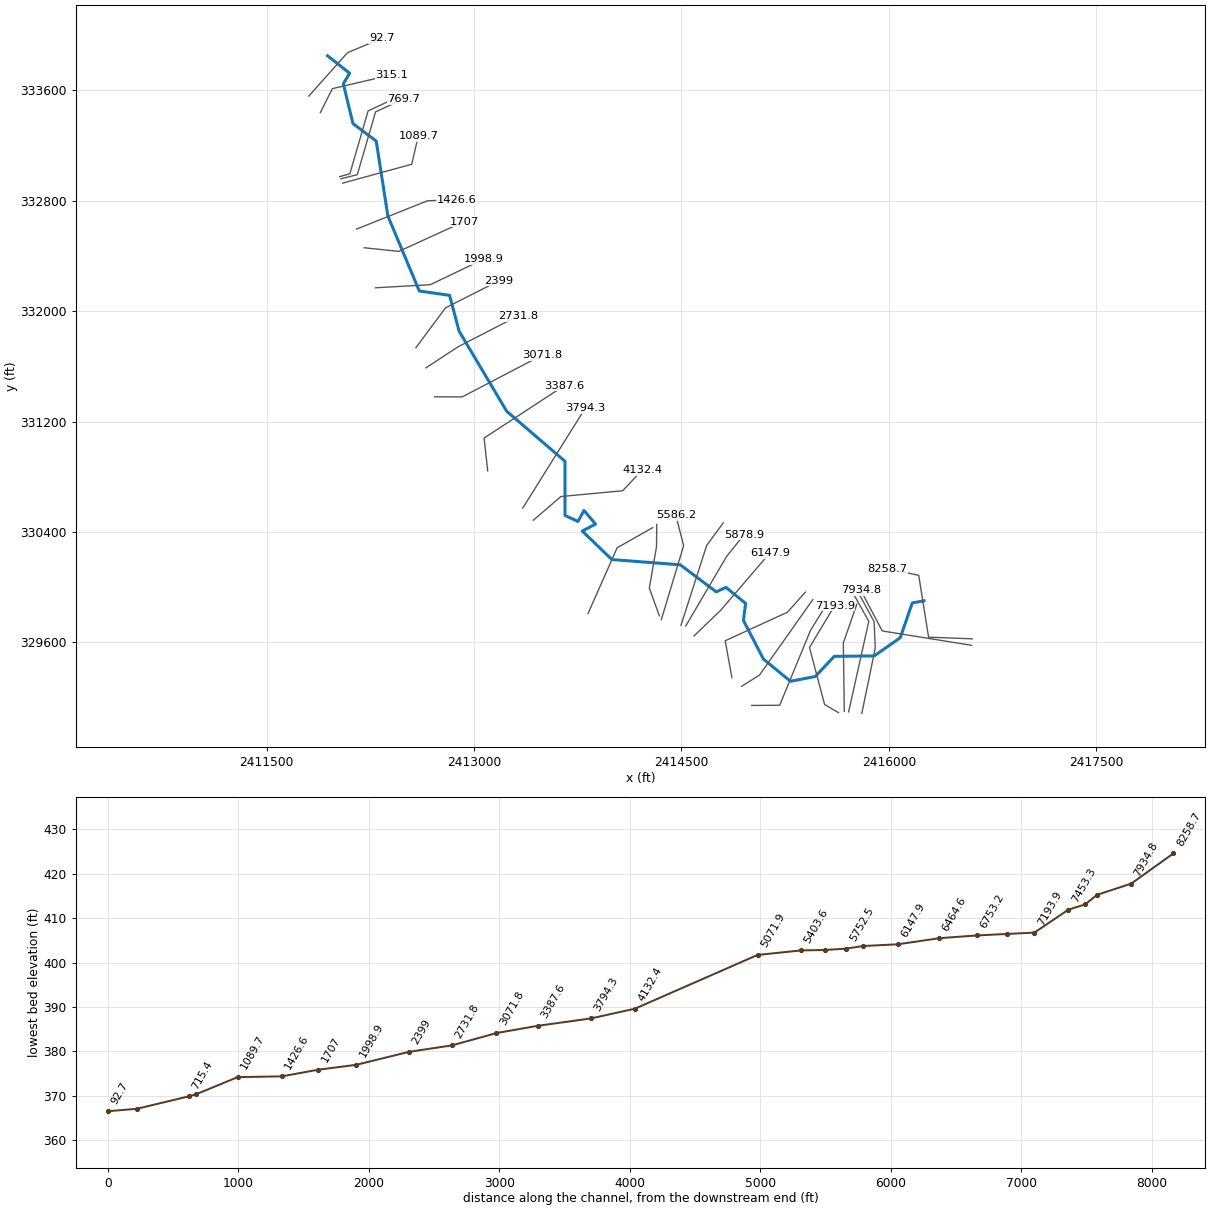
--- SHAWRUN.prj (project) ---

Proj Title=SHAWRUN
Current Plan=p01
Default Exp/Contr=0,0
English Units
Geom File=g01
Flow File=f01
Plan File=p01
BEGIN DESCRIPTION:
END DESCRIPTION:
DSS Export Rating Curves= 0
DSS Export Rating Curve Sorted= 0
DSS Export Volume Flow Curves= 0
DXF OffsetX= 0
DXF OffsetY= 0
DXF ScaleX= 0
DXF ScaleY= 0

--- SHAWRUN.p01 (plan) ---

Plan Title=Floodplain
Program Version=4.00
Geom File=g01
Flow File=f01
K Sum by GR=0
Std Step Tol=0.01
Critical Tol=0.01
Num of Std Step Trials=20
Max Error Tol=0.3
Flow Tol Ratio=0.001
Split Flow NTrial=30
Split Flow Tol=0.02
Split Flow Ratio=0.02
Log Output Level=0
Friction Slope Method=1
Unsteady Friction Slope Method=2
Unsteady Bridges Friction Slope Method=1
Global Log Level=0
CheckData=False
Run HTab=0
Run UNet=0
Run PostProcess=0
UNET Theta=0
UNET Theta Warmup=0
UNET ZTol=0
UNET ZSATol=0
UNET MxIter=0
UNET MaxInSteps=0
UNET DtIC=0
UNET DtMin=0
UNET MaxCRTS=0
UNET WFStab=0
UNET SFStab=0
UNET WFX=0
UNET SFX=0
UNET DSS MLevel=0
UNET DZMax Abort=0
UNET Convert EG Bridges=0
UNET Use Existing IB Tables=0
UNET Froude Limit=0
UNET Froude Power=0
Write IC File=0
Echo Input=False
Echo Output=False
Write Detailed=0

--- SHAWRUN.f01 (steady flow) ---

Flow Title=NFF Regression Equation
Program Version=5.03
Number of Profiles= 1
Profile Names=P100yr
River Rch & RM=SHAWRUN,Main            ,8258.7
 439.549
River Rch & RM=SHAWRUN,Main            ,7934.8
704.8045
River Rch & RM=SHAWRUN,Main            ,7453.3
 712.566
River Rch & RM=SHAWRUN,Main            ,7193.9
1053.441
River Rch & RM=SHAWRUN,Main            ,6753.2
 1604.77
River Rch & RM=SHAWRUN,Main            ,5071.9
1698.835
River Rch & RM=SHAWRUN,Main            ,92.7
1820.955
Boundary for River Rch & Prof#=SHAWRUN,Main            , 1
Up Type= 0
Dn Type= 3
Dn Slope=0.00265
DSS Import GetInterval= 0
DSS Import GetPeak= 0
DSS Import FillOption= 0

--- SHAWRUN.g01 (geometry) ---

Geom Title=USGS 10m DEM
Program Version=5.03

River Reach=SHAWRUN         ,Main
Reach XY= 30
     2416253.535      329901.331     2416168.466      329885.706
     2416081.978      329633.886     2415894.161      329502.025
      2415604.23      329498.553     2415467.077       329352.72
     2415288.258      329317.997     2415092.077      329479.456
      2414947.98      329758.969     2414963.605      329882.233
     2414821.244      329998.553       2414751.8      329965.567
     2414491.383      330161.747     2413996.591      330199.942
      2413783.05      330406.539     2413878.536      330456.886
     2413795.202      330555.844     2413751.799      330475.983
      2413658.05      330519.386      2413658.05      330911.747
     2413236.174      331274.595     2412892.424      331854.456
     2412823.327      332114.293     2412604.577      332145.544
     2412377.147      332689.814     2412293.177      333232.175
     2412124.774      333358.912     2412055.237      333646.875
      2412101.07      333723.264     2411941.348      333849.652

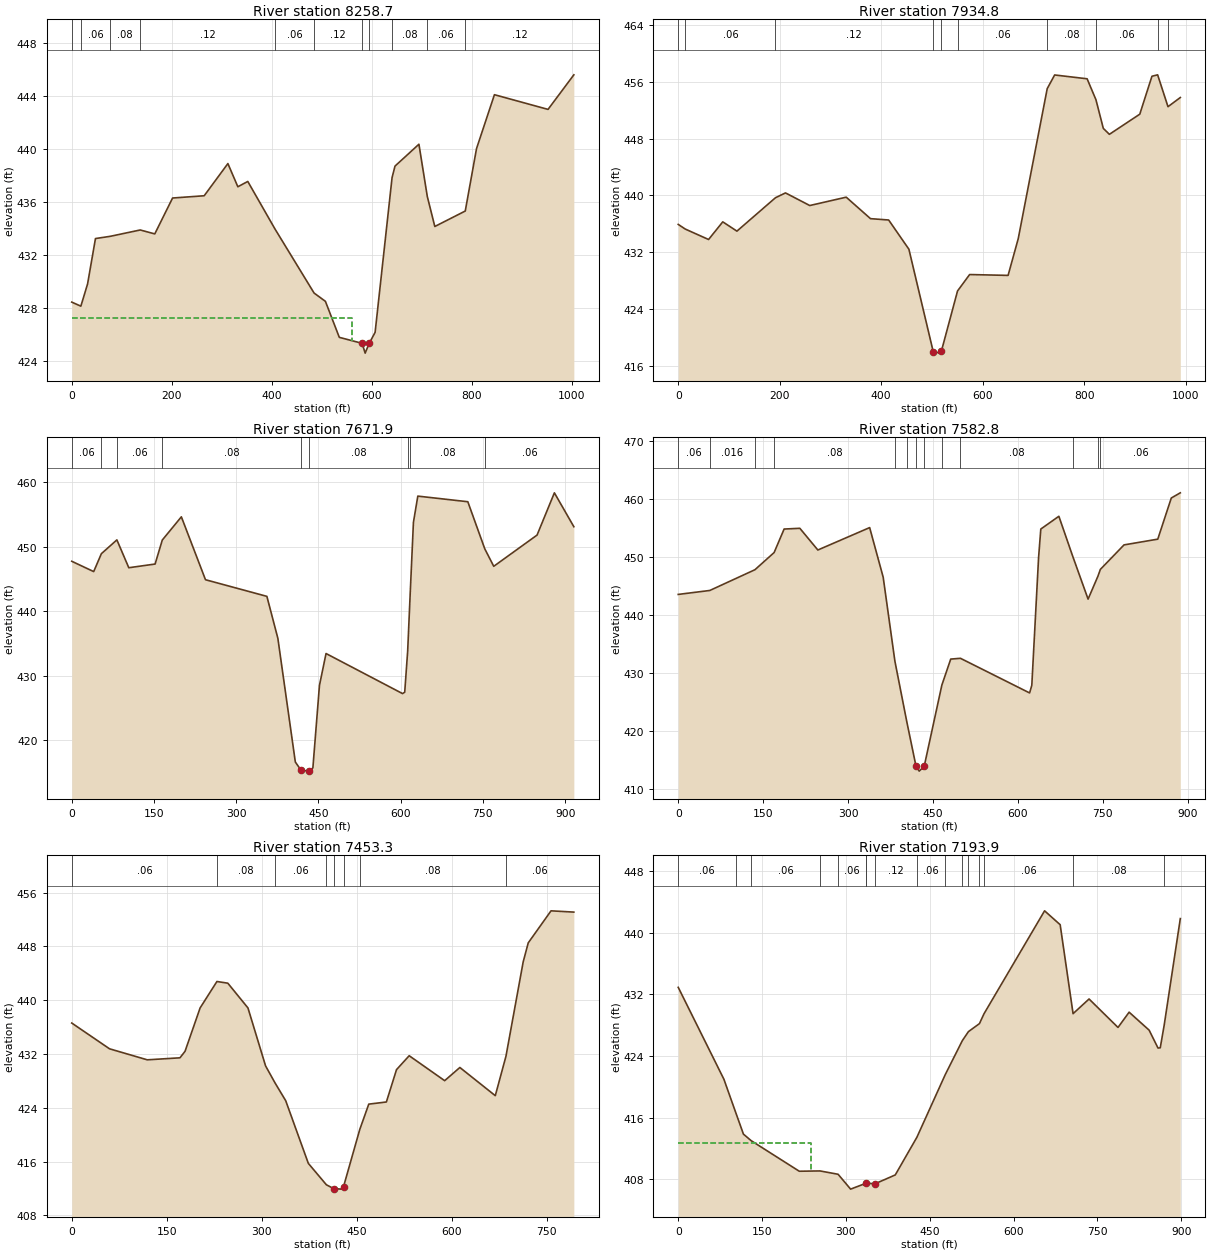
Type RM Length L Ch R = 1 ,8258.7  ,295.1,324,352.8
XS GIS Cut Line= 4
     2416602.517      329625.476     2416286.545      329637.628
     2416215.364      330085.545     2415986.198      330134.156
#Sta/Elev= 30
       0  428.44   18.17428.1352    31.6  429.81    47.4  433.24   76.67 433.406
  136.91433.8869     166  433.59   201.6   436.3   264.8  436.47   312.2   438.9
   332.1  437.15     352  437.55  406.45433.9562  484.56429.1253   507.2   428.5
     535  425.78  580.63425.3307   586.7  424.59   594.7  425.32   606.6  426.16
   640.5437.8403   646.4  438.71   694.2  440.36  710.99436.4091     726  434.15
  786.86435.3175   809.4  440.03   845.2   444.1   952.4  442.99    1004   445.6
#Mann= 11 ,-1 , 0
       0     .08       0   18.17     .06       0   76.67     .08       0
  136.91     .12       0  406.45     .06       0  484.56     .12       0
  580.63    .045       0   594.7     .12       0   640.5     .08       0
  710.99     .06       0  786.86     .12       0
#XS Ineff= 2 , 0
          560.99  427.25
Permanent Ineff=
       F       F
Bank Sta=580.63,594.7
XS Rating Curve= 0 ,0
Exp/Cntr=0.3,0.1

Type RM Length L Ch R = 1 ,7934.8  ,300.5,262.9,222.5
XS GIS Cut Line= 3
     2416597.309      329578.601     2415951.475      329682.767
     2415795.225      329979.642
#Sta/Elev= 30
       0  435.92   13.87435.2626    59.8  433.79    87.8  436.28   115.7  434.97
  191.67439.6796   211.4  440.36   259.3  438.58   331.1  439.76     379  436.73
   414.8  436.54   454.7  432.42   502.6  417.99   506.6  417.77   518.6  418.01
  550.56426.5324   574.4  428.85   650.2  428.73   670.2   433.9  727.34  455.06
     742  456.99     806  456.45  823.44453.4919   837.9  449.46   849.9  448.62
   909.8  451.46   933.8  456.81     945  457.01  965.42452.5162   989.7  453.81
#Mann= 10 ,-1 , 0
       0     .12       0   13.87     .06       0  191.67     .12       0
   502.6    .045       0   518.6     .12       0  550.56     .06       0
  727.34     .08       0  823.44     .06       0     945     .08       0
  965.42     .06       0
Bank Sta=502.6,518.6
XS Rating Curve= 0 ,0
Exp/Cntr=0.3,0.1

Type RM Length L Ch R = 1 ,7671.9  ,89.5,89.1,91.6
XS GIS Cut Line= 4
     2415803.906      329085.545     2415901.128      329559.503
     2415892.448      329750.476     2415777.864      329962.281
#Sta/Elev= 30
       0  447.77      40  446.17   53.97448.9413    82.3 451.085     104  446.77
     152  447.34  165.11451.0573   199.9  454.66   243.9  444.91   355.9  442.33
   375.9  435.84   407.8  416.65   418.2  415.38   431.8  415.24   433.2  415.26
   439.8  415.74   451.8  428.53   463.8  433.47   603.3  427.26   607.3  427.47
  612.68433.8247  617.13442.4042   623.2   453.8   631.2  457.87   722.4     457
  753.36449.6948   769.7  446.99   848.7  451.83   880.3  458.38   915.8  453.13
#Mann= 9 ,-1 , 0
       0     .06       0   53.97     .08       0    82.3     .06       0
  165.11     .08       0   418.2    .045       0   433.2     .08       0
  612.68     .06       0  617.13     .08       0  753.36     .06       0
Bank Sta=418.2,433.2
XS Rating Curve= 0 ,0
Exp/Cntr=0.3,0.1

Type RM Length L Ch R = 1 ,7582.8  ,124.2,129.5,134.7
XS GIS Cut Line= 3
      2415708.42      329095.962     2415854.253      329752.212
     2415750.086      329939.712
#Sta/Elev= 30
       0  443.54   55.78  444.22   135.5 447.795   169.4450.7544     187   454.8
   214.8  454.93   246.6  451.19   338.1  455.05     362  446.51  382.72432.0264
  403.54421.6886  419.75414.0537   425.6   413.1  434.49 413.947  465.65427.9287
   481.3   432.4  498.52 432.534   620.6  426.57   624.5  427.88   636.5  449.92
   640.4   454.8   672.3     457  696.63450.1511   723.9  442.73  741.31446.6819
   745.6447.8523   787.4  452.07     847  453.06   870.9  460.15   886.8  461.04
#Mann= 13 ,-1 , 0
       0     .06       0   55.78    .016       0   135.5     .06       0
   169.4     .08       0  382.72     .12       0  403.54     .08       0
  419.75    .045       0  434.49     .08       0  465.65     .12       0
  498.52     .08       0  696.63     .06       0  741.31     .08       0
   745.6     .06       0
Bank Sta=419.75,434.49
XS Rating Curve= 0 ,0
Exp/Cntr=0.3,0.1

Type RM Length L Ch R = 1 ,7453.3  ,255.9,259.4,251.3
XS GIS Cut Line= 3
      2415677.17      329099.434     2415670.225      329595.962
     2415767.448      329875.476
#Sta/Elev= 30
       0  436.61    59.6  432.78   119.2  431.14   170.8  431.44   178.8  432.41
   202.6  438.86  229.11442.7897   246.3  442.54   278.1  438.86   305.9  430.24
  320.57427.7506   337.7  425.06   373.4  415.74   401.9 412.557   413.2     412
   425.1  411.91     429  412.29  454.64420.7937   468.8  424.55   496.6  424.87
   512.6  429.68   532.6  431.75   588.6  428.04   612.6     430   668.5  425.81
  685.35431.6686   712.5  445.69   720.5  448.53   756.5   453.3   792.5  453.11
#Mann= 8 ,-1 , 0
       0     .06       0  229.11     .08       0  320.57     .06       0
   401.9     .12       0   413.2    .045       0     429     .12       0
  454.64     .08       0  685.35     .06       0
Bank Sta=413.2,429
XS Rating Curve= 0 ,0
Exp/Cntr=0.3,0.1

Type RM Length L Ch R = 1 ,7193.9  ,221.1,208.4,206.9
XS GIS Cut Line= 4
     2415635.503      329090.753     2415534.809      329149.781
     2415425.434      329562.976     2415607.725      329866.795
#Sta/Elev= 30
       0   432.9    81.7  420.99  103.29 416.587   116.7  413.87   130.6413.0165
   216.6  409.06   253.7 409.098  286.06408.6663   308.5  406.74  336.38407.5101
   336.4  407.51   352.4  407.44   388.4  408.58  427.16413.4719  477.73 421.568
   508.4 425.988  519.31427.1567  539.07428.1997   547.2429.4746   655.6  442.82
   683.5  441.02  706.59429.4865   735.2  431.39     787   427.7   806.9  429.68
   842.7  427.35   858.6  425.03   862.6  425.06  869.56427.9586   898.5  441.81
#Mann= 16 ,-1 , 0
       0     .06       0  103.29     .12       0   130.6     .06       0
   253.7     .12       0  286.06     .06       0  336.38     .12       0
   336.4    .045       0   352.4     .12       0  427.16     .06       0
  477.73     .12       0   508.4     .08       0  519.31     .06       0
  539.07     .08       0   547.2     .06       0  706.59     .08       0
  869.56     .06       0
#XS Ineff= 2 , 0
          237.36  412.77
Permanent Ineff=
       F       F
Bank Sta=336.4,352.4
XS Rating Curve= 0 ,0
Exp/Cntr=0.3,0.1

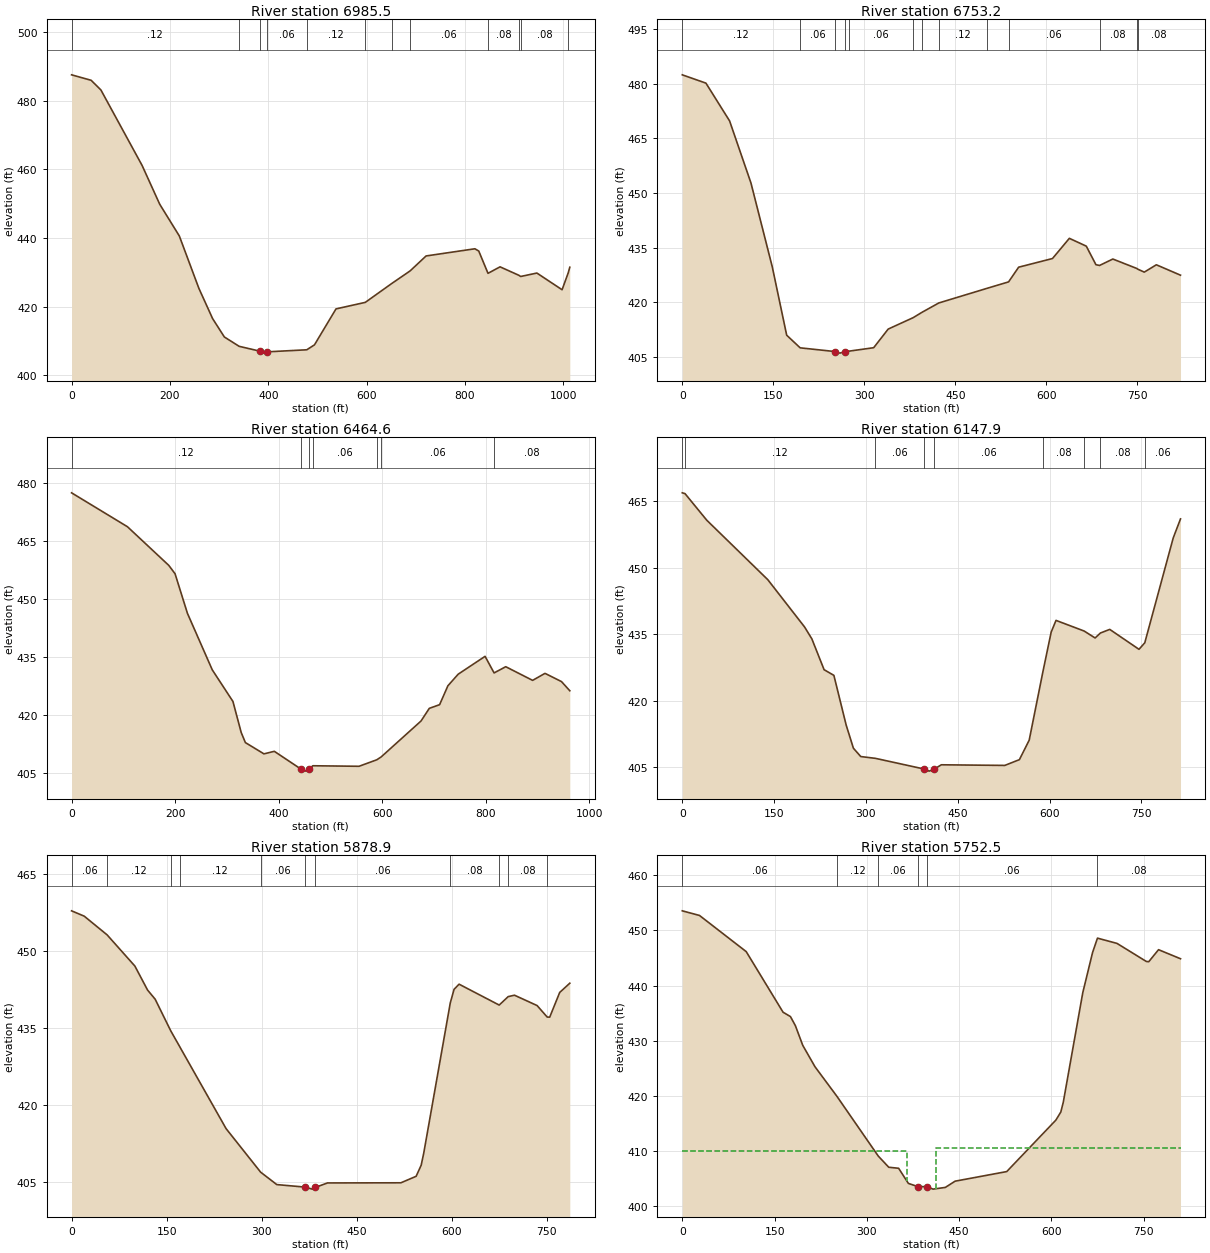
Type RM Length L Ch R = 1 ,6985.5  ,236,232.3,228
XS GIS Cut Line= 4
     2415007.031      329142.837     2415210.156      329144.573
     2415432.378      329686.239     2415550.434      329877.212
#Sta/Elev= 30
       0  487.49    39.8   485.9    59.7  483.07   143.4   461.1   179.2  449.81
   219.1  440.56   258.9  425.29   286.8  416.49   310.7  411.14  340.76408.4214
   382.4  407.03   390.3  406.44   398.3  406.82  478.29407.4122   493.9  408.85
   537.7  419.32  597.22421.2206   650.9426.7035  688.53430.4022   720.9  434.74
   820.1  436.83     828  436.17  846.75429.6821   871.3  431.57  909.69429.0951
  913.19428.7585   946.2  429.76   997.4   424.9 1009.86429.8068  1013.1  431.46
#Mann= 12 ,-1 , 0
       0     .12       0  340.76     .06       0   382.4    .045       0
   398.3     .06       0  478.29     .12       0  597.22     .06       0
   650.9     .08       0  688.53     .06       0  846.75     .08       0
  909.69     .06       0  913.19     .08       0 1009.86     .06       0
Bank Sta=382.4,398.3
XS Rating Curve= 0 ,0
Exp/Cntr=0.3,0.1

Type RM Length L Ch R = 1 ,6753.2  ,301.6,288.6,275.6
XS GIS Cut Line= 3
      2414935.85      329281.726     2415064.323      329363.323
     2415449.739      329910.198
#Sta/Elev= 30
       0  482.47      39  480.19      78  469.82   113.2  452.79   148.3   429.8
   172.1  411.02  194.28407.5535   251.8  406.53   259.7   406.1   267.7  406.49
  275.56406.6595   315.5  407.59   339.4   412.7   380.5415.8268  394.95 417.285
  422.88419.8689  502.03423.8669  537.85425.6503   554.4  429.68   610.2  432.06
     638   437.6   665.9  435.46   681.8  430.37  687.73430.1571   709.7  431.92
  748.98429.3458  751.22429.1031   761.5  428.33   781.4  430.34   821.2  427.49
#Mann= 13 ,-1 , 0
       0     .12       0  194.28     .06       0   251.8    .045       0
   267.7     .12       0  275.56     .06       0   380.5     .12       0
  394.95     .06       0  422.88     .12       0  502.03     .06       0
  537.85     .06       0  687.73     .08       0  748.98     .06       0
  751.22     .08       0
Bank Sta=251.8,267.7
XS Rating Curve= 0 ,0
Exp/Cntr=0.3,0.1

Type RM Length L Ch R = 1 ,6464.6  ,306.7,316.7,326.5
XS GIS Cut Line= 4
      2414864.67      329344.226     2414816.059      329611.587
     2415265.711      329818.184      2415395.92      329964.017
#Sta/Elev= 30
       0  477.39   107.9  468.63   187.8  458.63   199.8  456.49   223.8  446.23
   271.7  431.65   311.6  423.48   327.6  415.45   335.6  412.86   371.5  409.94
   391.5   410.6   443.3  405.98   451.3  405.48   459.3   406.1  465.98406.8681
   555.1  406.73  589.51408.4182  597.84409.1495   674.8  418.43   690.8   421.7
   710.7  422.65   726.7  427.53   746.6  430.53   798.5  435.14   815.9430.8545
   838.4  432.46   890.3  428.93   914.2  430.74   946.1  428.61   962.1  426.25
#Mann= 7 ,-1 , 0
       0     .12       0   443.3    .045       0   459.3     .12       0
  465.98     .06       0  589.51     .12       0  597.84     .06       0
   815.9     .08       0
Bank Sta=443.3,459.3
XS Rating Curve= 0 ,0
Exp/Cntr=0.3,0.1

Type RM Length L Ch R = 1 ,6147.9  ,258,269,257.9
XS GIS Cut Line= 3
     2414590.364      329646.309     2414783.073      329832.073
     2415138.464      330247.076
#Sta/Elev= 30
       0  466.94    4.47466.7595      40  460.76   139.8  447.32   199.8  436.66
   211.7  433.97   231.7  427.01   247.7  425.73   267.7  414.54   279.6  409.28
   291.6   407.4  315.59406.9955   395.3  404.58   403.3  404.11   411.2  404.53
   423.2  405.54   526.9   405.4   550.8   406.7   566.8   411.1  589.33426.6391
   602.7  435.49   610.6  438.14  656.56435.7412   674.5  434.17  683.12435.2854
   698.4  436.11   746.2  431.61  755.65433.0872   802.1  456.75     814  461.05
#Mann= 9 ,-1 , 0
       0     .08       0    4.47     .12       0  315.59     .06       0
   395.3    .045       0   411.2     .06       0  589.33     .08       0
  656.56     .06       0  683.12     .08       0  755.65     .06       0
Bank Sta=395.3,411.2
XS Rating Curve= 0 ,0
Exp/Cntr=0.3,0.1

Type RM Length L Ch R = 1 ,5878.9  ,118.3,126.4,137.6
XS GIS Cut Line= 3
     2414531.336      329719.226     2414826.475      330222.698
     2414953.211      330380.684
#Sta/Elev= 30
       0  457.77      20  456.73   56.09453.0972    99.9  447.04   119.9  442.38
   131.9   440.6  156.64434.4216  170.85431.3321   243.8  415.46  298.27407.0083
   323.8  404.59   368.7   404.1   379.7  403.71  384.77404.0471   403.7  404.91
   519.6  404.94   543.6   406.2   551.6  408.35   555.6  410.67  597.55439.8967
   603.5  442.52   611.4  443.52  674.69 439.464  688.88441.1026   698.8  441.38
   734.5  439.37  750.49437.1298   754.4  437.12   770.2  441.92   786.1  443.71
#Mann= 11 ,-1 , 0
       0     .06       0   56.09     .12       0  156.64     .06       0
  170.85     .12       0  298.27     .06       0   368.7    .045       0
  384.77     .06       0  597.55     .08       0  674.69     .06       0
  688.88     .08       0  750.49     .06       0
Bank Sta=368.7,384.77
XS Rating Curve= 0 ,0
Exp/Cntr=0.3,0.1

Type RM Length L Ch R = 1 ,5752.5  ,169.5,166.2,160.2
XS GIS Cut Line= 3
     2414496.614      329724.434     2414682.378      330302.559
      2414802.17      330465.753
#Sta/Elev= 30
       0  453.55      28  452.71   103.9  446.16   163.8  435.18   175.8  434.39
   183.8  432.75   195.8  429.18   215.7   425.3  251.33419.9446  318.53409.1178
   335.6  407.09   351.6  406.91   367.5  404.16   382.9  403.59   397.9  403.58
   407.5  403.13   427.5  403.44   443.4  404.57   527.3  406.31   607.2  415.64
   615.2   417.1   619.2  418.87   650.9  438.73   666.8     446  674.76448.6013
   706.5  447.65   754.1  444.38   758.1  444.33     774  446.51   809.7  444.87
#Mann= 6 ,-1 , 0
       0     .06       0  251.33     .12       0  318.53     .06       0
   382.9    .045       0   397.9     .06       0  674.76     .08       0
#XS Ineff= 2 , 0
          365.33  410.03   412.8          410.54
Permanent Ineff=
       F       F
Bank Sta=382.9,397.9
XS Rating Curve= 0 ,0
Exp/Cntr=0.3,0.1

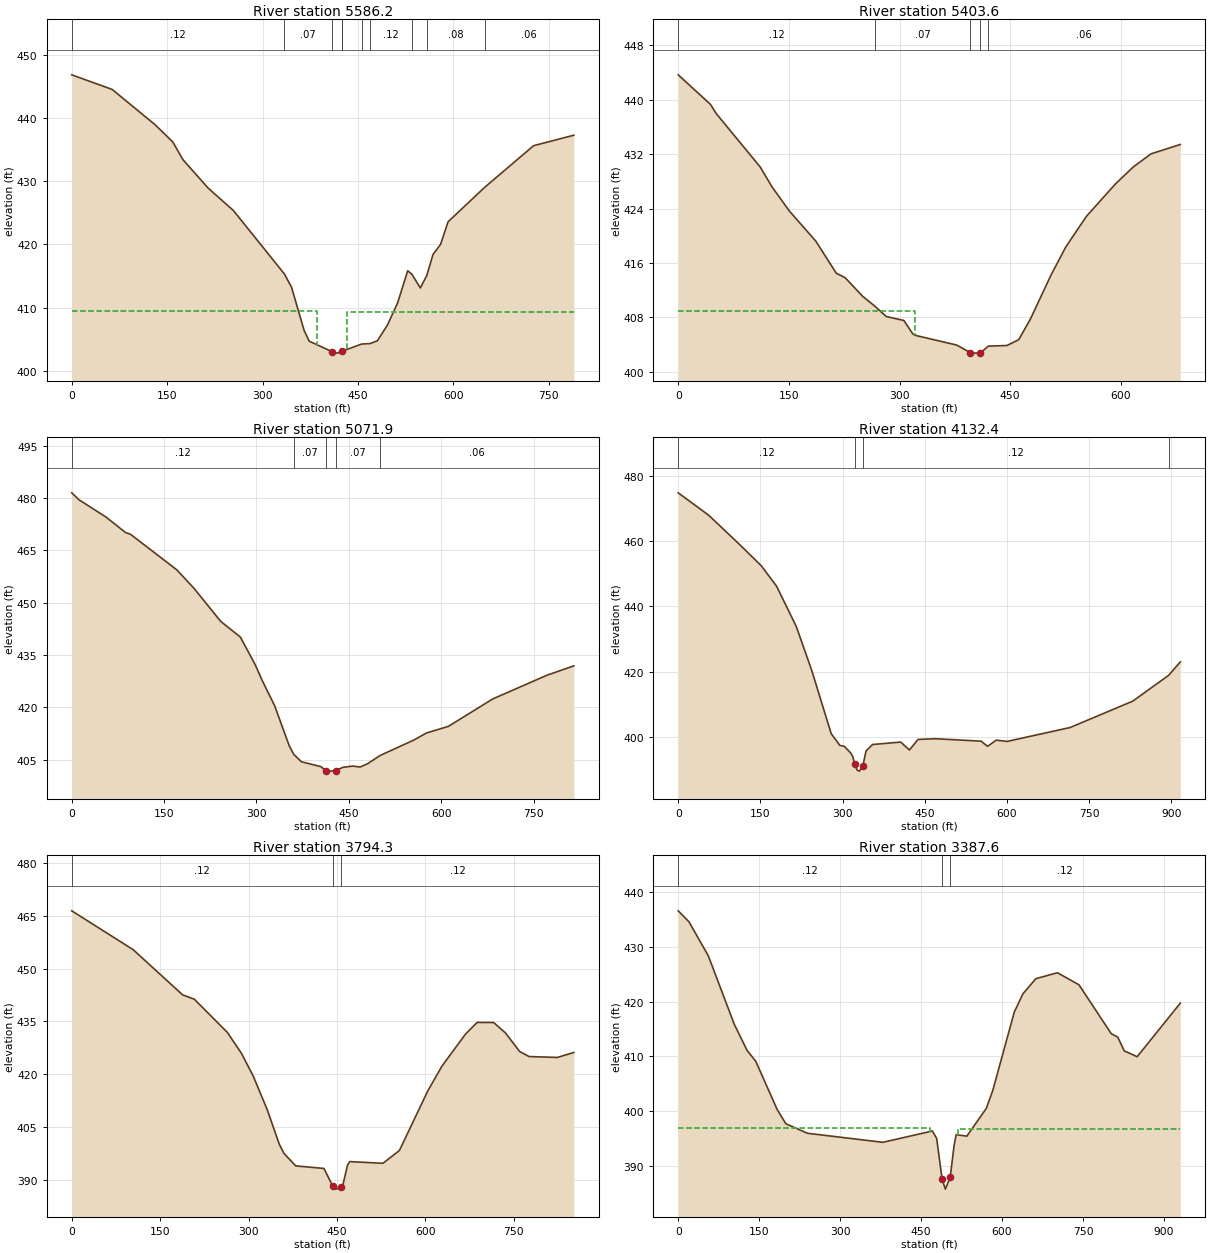
Type RM Length L Ch R = 1 ,5586.2  ,179.7,182.6,185.1
XS GIS Cut Line= 3
     2414354.253      329764.364     2414515.711      330300.823
      2414458.42      330523.045
#Sta/Elev= 30
       0   446.8    63.6  444.49   131.1  438.91   158.9  436.19   174.8   433.4
   214.6  428.89   254.3  425.35  334.49415.3245   345.7  413.23   365.5   406.4
   373.5  404.71   409.2  403.06   417.2  402.82   425.1  403.09  425.38403.1278
  456.04404.2556  469.33404.3279   480.8  404.78   496.7  407.29   512.6  410.78
   528.4  415.84  534.93415.2887   548.3  413.12  558.49415.1114   568.1  418.39
     580  419.99   591.9  423.58  649.57429.0313   726.4   435.6   789.7  437.26
#Mann= 10 ,-1 , 0
       0     .12       0  334.49     .07       0   409.2    .045       0
   425.1     .07       0  425.38     .12       0  456.04     .06       0
  469.33     .12       0  534.93     .06       0  558.49     .08       0
  649.57     .06       0
#XS Ineff= 2 , 0
          385.55  409.54  433.44          409.29
Permanent Ineff=
       F       F
Bank Sta=409.2,425.1
XS Rating Curve= 0 ,0
Exp/Cntr=0.3,0.1

Type RM Length L Ch R = 1 ,5403.6  ,336,331.7,328.8
XS GIS Cut Line= 4
     2414340.364      329792.142     2414267.448      329993.531
     2414319.531      330292.142     2414321.267      330455.337
#Sta/Elev= 30
       0  443.67    43.6  439.33    51.6  437.96   111.1  430.11   126.9  427.22
   150.7  423.62   186.4  419.21   214.2  414.48   226.2  413.82   250.1  411.07
  266.24  409.65     282  408.11   305.9  407.52   317.9  405.55   321.9  405.32
   377.7   403.9     396402.7751   400.3  402.72   409.6  402.75  420.22403.7486
   445.5  403.84   461.5   404.7   477.4  407.75   505.3  414.22   525.3  418.34
   553.1  422.83   592.9  427.65   616.8  430.12   640.7  432.04   680.5  433.42
#Mann= 5 ,-1 , 0
       0     .12       0  266.24     .07       0     396    .045       0
   409.6     .07       0  420.22     .06       0
#XS Ineff= 2 , 0
          321.47  408.95
Permanent Ineff=
       F       F
Bank Sta=396,409.6
XS Rating Curve= 0 ,0
Exp/Cntr=0.3,0.1

Type RM Length L Ch R = 1 ,5071.9  ,973.9,939.5,850.1
XS GIS Cut Line= 3
     2413824.739      329809.503     2414034.809      330285.198
     2414291.753      330431.031
#Sta/Elev= 30
       0  481.49    11.9  479.47    55.6  474.55    87.3  470.11    95.3  469.62
   170.7   459.4   198.5  454.12   242.1   444.6   273.9  440.13   297.7  432.31
   309.6  427.59   329.5  420.47   353.3  408.93  360.68406.4787   373.1  404.38
   404.9  402.97   412.8  401.78   418.9   401.7   428.7  401.86   440.6   402.8
   456.5  403.15   468.4  402.88   480.3  403.81  500.85406.1866     556  410.64
   575.9  412.62   611.8  414.54   683.7  422.39   771.5  429.17   815.5  431.89
#Mann= 5 ,-1 , 0
       0     .12       0  360.68     .07       0   412.8    .045       0
   428.7     .07       0  500.85     .06       0
Bank Sta=412.8,428.7
XS Rating Curve= 0 ,0
Exp/Cntr=0.3,0.1

Type RM Length L Ch R = 1 ,4132.4  ,317,338.1,359.5
XS GIS Cut Line= 4
     2413428.906      330484.851     2413628.559      330656.726
     2414074.739      330698.392     2414215.364      330847.698
#Sta/Elev= 30
       0  474.73    55.9  467.84   111.8  458.96   151.7   452.4   179.6  446.16
   215.5  433.85   243.5  420.54   279.3  401.06   295.2  397.45   303.1  397.19
     315  395.11     319  393.91   322.2  391.62   326.9  389.86   330.9  389.59
   337.2  391.31   342.8  395.71   354.6  397.73   406.2  398.48   422.1  396.06
   437.9  399.29   469.7   399.5   552.9  398.76   564.8  397.19   580.7  399.07
   600.5  398.68   715.5  402.93   829.9     411  895.27 418.877   916.7     423
#Mann= 4 ,-1 , 0
       0     .12       0   322.2    .045       0   337.2     .12       0
  895.27     .06       0
Bank Sta=322.2,337.2
XS Rating Curve= 0 ,0
Exp/Cntr=0.3,0.1

Type RM Length L Ch R = 1 ,3794.3  ,416.5,406.7,396.8
XS GIS Cut Line= 2
     2413352.517      330573.392     2413803.906      331295.614
#Sta/Elev= 30
       0  466.37     104  455.37   187.9  442.54   207.9  441.29   263.9  431.88
   287.9  425.91   307.9  419.45   331.9   409.8   351.9  400.19   359.9  397.53
   379.9  393.99   427.8  393.26   442.3  388.38   447.8  387.39   457.3   387.9
   459.8  388.46   467.8  394.25   471.8   395.2   527.8  394.72   555.8  398.35
   603.8  415.21   627.8  422.26   667.8  431.37   687.7   434.7   715.7  434.67
   735.7  431.72   759.7  426.46   775.7  425.02   823.7  424.76   851.7  426.17
#Mann= 3 ,-1 , 0
       0     .12       0   442.3    .045       0   457.3     .12       0
Bank Sta=442.3,457.3
XS Rating Curve= 0 ,0
Exp/Cntr=0.3,0.1

Type RM Length L Ch R = 1 ,3387.6  ,318,315.8,313.6
XS GIS Cut Line= 3
     2413099.045      330842.489     2413073.003      331080.337
     2413651.128      331458.809
#Sta/Elev= 30
       0  436.57    19.9  434.57    55.8  428.34   103.7  415.88   127.6  411.06
   143.6   409.1   183.4  400.26   199.4  397.68   239.3  395.94   379.1  394.28
   470.9  396.35   478.9  394.98   488.9  387.55   494.9  385.73   503.9  387.86
   510.9  393.55   514.9  395.67   534.8  395.41   570.8  400.47   582.8  403.75
   622.7  418.08   638.7  421.41   662.6  424.17   702.6  425.26   742.5  423.06
   802.4  414.12   814.4   413.5   826.4  410.99   850.4  409.92   930.3  419.71
#Mann= 3 ,-1 , 0
       0     .12       0   488.9    .045       0   503.9     .12       0
#XS Ineff= 2 , 0
          466.46  396.93  518.06          396.72
Permanent Ineff=
       F       F
Bank Sta=488.9,503.9
XS Rating Curve= 0 ,0
Exp/Cntr=0.3,0.1

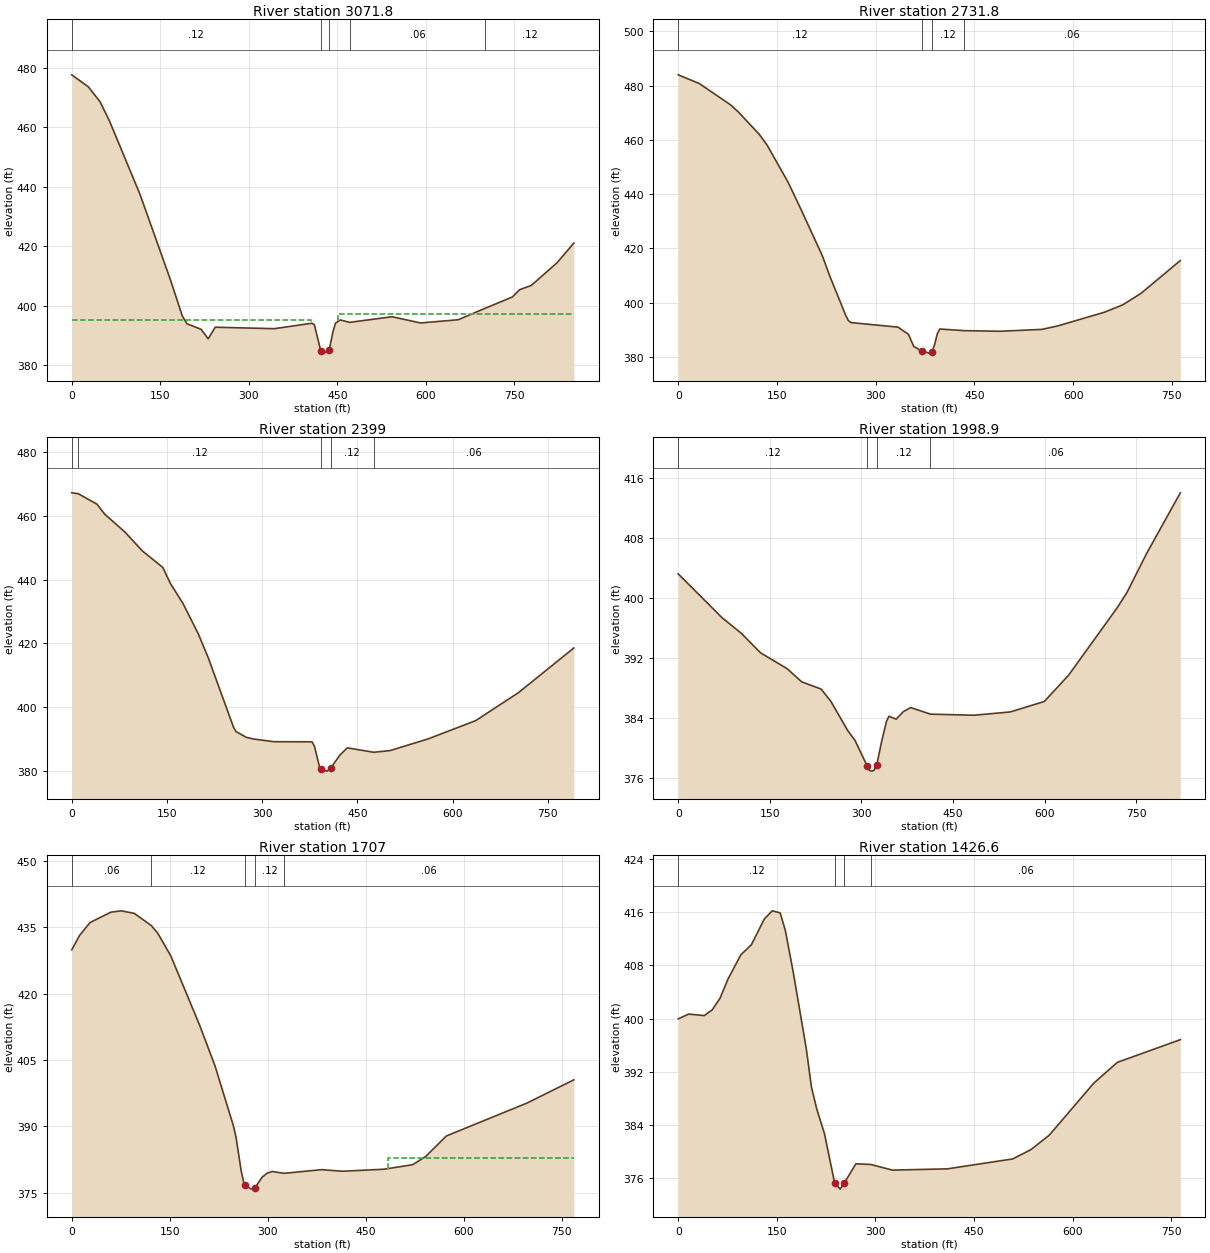
Type RM Length L Ch R = 1 ,3071.8  ,340.4,340,339.8
XS GIS Cut Line= 3
     2412715.364      331378.948     2412914.499      331378.201
     2413491.644      331680.266
#Sta/Elev= 30
       0  477.56    27.9  473.56    47.8  468.56    63.7  462.15   115.5  437.48
   167.3  408.66   187.2  396.62   195.2  393.95   219.1  392.11   231.1  388.91
   243.1   392.8     343  392.31     407  394.14     411  393.66  421.76 384.959
   426.9   384.1  435.92385.0595   442.9  391.58   446.9  394.19   454.9  395.24
  470.76394.4366   542.8  396.32   590.8  394.23   654.7  395.31  700.76399.1927
   746.6  402.97   758.6  405.39   778.6  406.84   822.6  414.54   850.6  421.07
#Mann= 5 ,-1 , 0
       0     .12       0  421.76    .045       0  435.92     .12       0
  470.76     .06       0  700.76     .12       0
#XS Ineff= 2 , 0
          405.57   395.2  450.98          397.23
Permanent Ineff=
       F       F
Bank Sta=421.76,435.92
XS Rating Curve= 0 ,0
Exp/Cntr=0.3,0.1

Type RM Length L Ch R = 1 ,2731.8  ,333,332.8,332.5
XS GIS Cut Line= 3
     2412652.864      331589.017     2412885.503      331741.795
     2413316.059      331964.017
#Sta/Elev= 30
       0  484.01    31.8  480.82    79.5  472.94    91.4  470.29   123.3     462
   135.2  458.02     167  444.34   186.9  434.17   218.7  417.39   230.6  409.56
   254.5  395.24   258.4  393.38   262.4   392.6   333.9  390.92   349.8  388.26
   357.8  383.81   369.7  382.12   381.6  381.33   385.6  381.84   389.5  384.42
   393.5  388.42   397.5  390.22  434.59389.6218   488.8  389.39   552.4  390.09
   576.2  391.34   647.7  396.43   675.5  399.16   703.3  403.42   762.8  415.49
#Mann= 4 ,-1 , 0
       0     .12       0   369.7    .045       0   385.6     .12       0
  434.59     .06       0
Bank Sta=369.7,385.6
XS Rating Curve= 0 ,0
Exp/Cntr=0.3,0.1

Type RM Length L Ch R = 1 ,2399    ,407.6,400.1,328.8
XS GIS Cut Line= 3
     2412579.948      331734.851     2412793.489      332023.045
     2413178.906      332219.226
#Sta/Elev= 30
       0  467.27   10.13467.0095    39.8   463.7    51.8   460.6    83.7  454.97
   111.6  448.96   143.5  443.83   155.4  438.82   175.4  432.45   199.3  423.02
   215.2  415.41   255.1  393.54     259  392.26     275  390.47     287  389.92
   318.8  389.09   378.5  389.06   382.5  387.65   390.4  381.18   393.2  380.47
   402.3  379.85   408.2  380.84   422.2  384.81   434.1  387.16  475.83385.7748
   501.5   386.3     561  389.93   636.4   395.7   703.9  404.49   791.2  418.54
#Mann= 5 ,-1 , 0
       0     .08       0   10.13     .12       0   393.2    .045       0
   408.2     .12       0  475.83     .06       0
Bank Sta=393.2,408.2
XS Rating Curve= 0 ,0
Exp/Cntr=0.3,0.1

Type RM Length L Ch R = 1 ,1998.9  ,283.9,291.9,331.1
XS GIS Cut Line= 3
     2412288.281      332168.878     2412684.114      332191.448
     2413067.795      332375.476
#Sta/Elev= 30
       0  403.21    71.4   397.4   103.1  395.31   134.8   392.7   178.4  390.58
   202.2  388.83   233.9  387.88   249.8  386.25   277.5  382.35   289.4  381.04
   309.2  377.66   313.2  377.03   317.2  376.95   321.2   377.1   325.1   377.8
     333   380.9     341  383.58   344.9  384.25   356.8  383.87   368.7  384.88
   380.6  385.41  412.95384.5386     484  384.39   543.6  384.83   599.3  386.22
   639.1  389.72   718.6  398.69   734.5  400.71   766.3  405.84     822     414
#Mann= 4 ,-1 , 0
       0     .12       0   309.2    .045       0   325.1     .12       0
  412.95     .06       0
Bank Sta=309.2,325.1
XS Rating Curve= 0 ,0
Exp/Cntr=0.3,0.1

Type RM Length L Ch R = 1 ,1707    ,281,280.5,279.1
XS GIS Cut Line= 3
     2412206.684      332458.809     2412456.684      332432.767
      2412927.17      332648.045
#Sta/Elev= 30
       0  429.93      12  433.18    27.9  436.08    59.8  438.42    75.8  438.73
    95.8  438.15  121.56435.4271   131.7  433.67   151.6  428.56   195.5     413
   219.4  403.67   247.4   390.2   251.4  387.69   259.3  380.06   263.3  377.33
   265.6  376.67   275.2  375.84   280.6  376.15   291.2  378.49   299.1  379.44
   307.1  379.82  324.91379.4118   382.7  380.24   414.5  379.88   478.2  380.34
     522  381.36   541.9  383.21   573.7  387.86   697.1  395.29   768.8  400.54
#Mann= 5 ,-1 , 0
       0     .06       0  121.56     .12       0   265.6    .045       0
   280.6     .12       0  324.91     .06       0
#XS Ineff= 2 , 0
                          484.62          382.77
Permanent Ineff=
       F       F
Bank Sta=265.6,280.6
XS Rating Curve= 0 ,0
Exp/Cntr=0.3,0.1

Type RM Length L Ch R = 1 ,1426.6  ,339.5,336.9,334.1
XS GIS Cut Line= 3
     2412151.128      332594.226     2412663.915      332799.236
     2412875.086      332807.767
#Sta/Elev= 30
       0  399.95    15.9  400.67    39.7  400.44    51.6   401.3    63.6  403.05
    75.5   405.9    95.4  409.61   111.2  411.09   131.1     415     143   416.2
     155  415.89   162.9  413.25   174.8  407.03   194.7  395.49   202.6   389.7
   210.6  386.41   222.5  382.65   237.8  375.29   246.3  374.34   252.8   375.3
   270.2  378.15  292.69378.0497   325.8   377.2   409.2  377.39   508.6  378.88
   536.4  380.28   564.2  382.45     632  390.28   667.9  393.41   763.6  396.82
#Mann= 4 ,-1 , 0
       0     .12       0   237.8    .045       0   252.8     .12       0
  292.69     .06       0
Bank Sta=237.8,252.8
XS Rating Curve= 0 ,0
Exp/Cntr=0.3,0.1

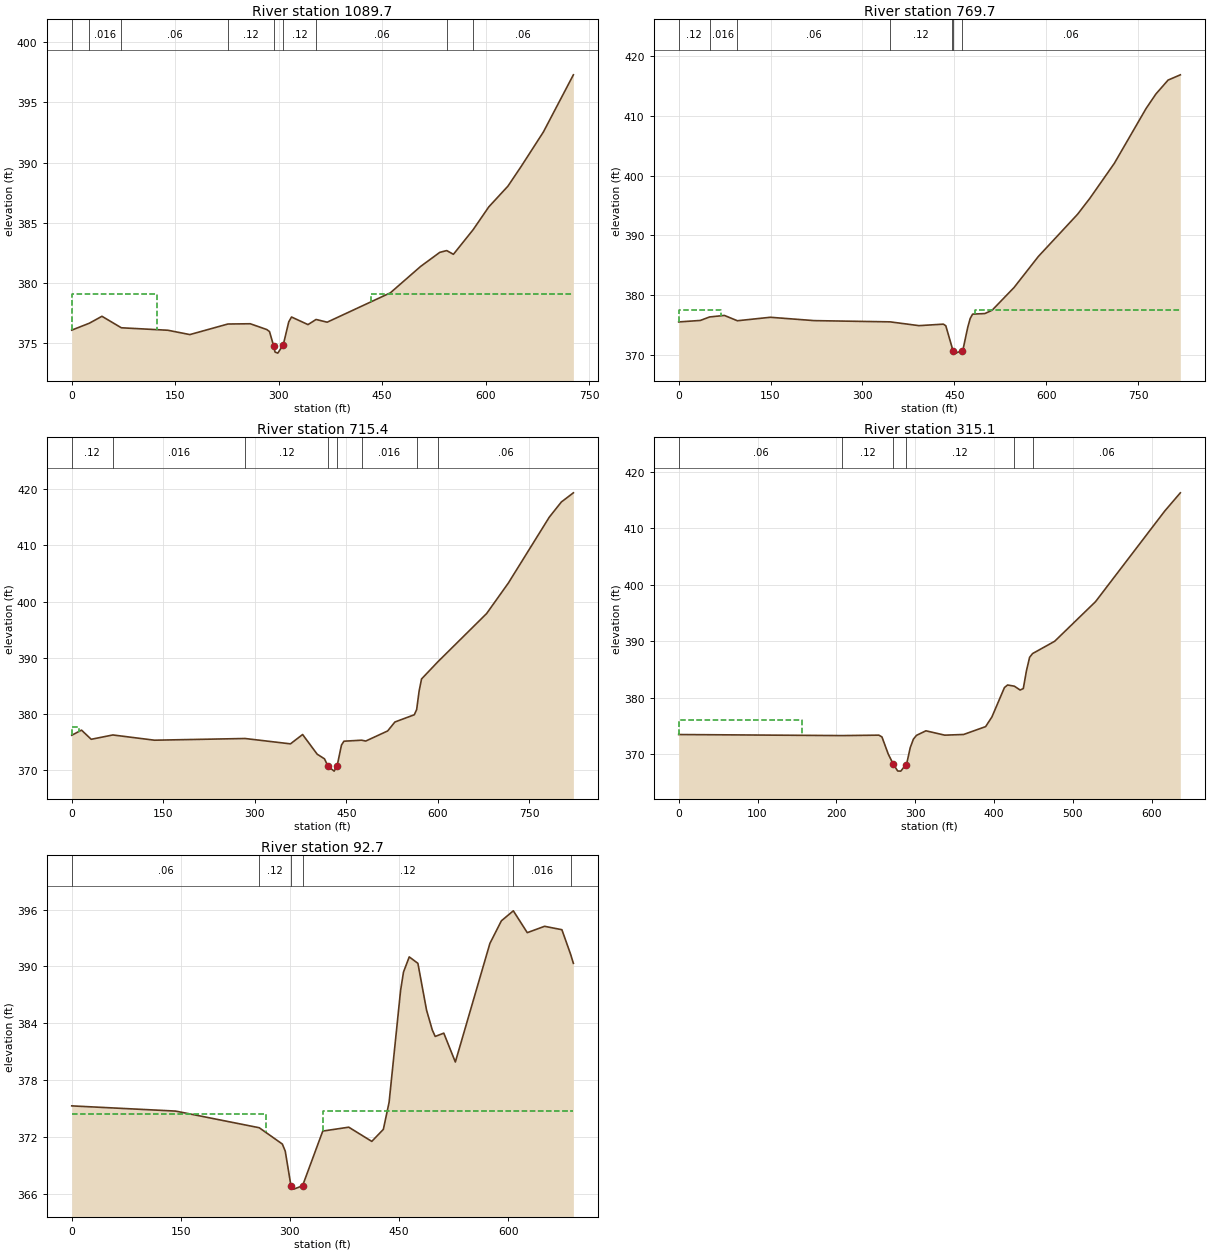
Type RM Length L Ch R = 1 ,1089.7  ,287.8,320,344
XS GIS Cut Line= 3
     2412050.418       332927.14     2412549.737      333063.786
     2412597.309      333267.837
#Sta/Elev= 30
       0  376.08   25.54376.6566    43.8  377.23    71.9 376.276   139.4  376.07
   171.2  375.71  226.35376.5884   258.8  376.61   282.7  376.13   286.7  375.96
  292.58374.7948   294.7  374.26   298.7  374.17   306.6  374.85   314.6  376.77
   318.6  377.17   342.5  376.54  354.19376.9658   370.3  376.74   461.9  379.18
   505.7  381.37   533.5  382.54  543.52382.6894   553.3  382.38  581.79384.4167
   604.6  386.32   632.3  388.04   652.1  389.73   683.7  392.54   727.2  397.29
#Mann= 9 ,-1 , 0
       0     .12       0   25.54    .016       0    71.9     .06       0
  226.35     .12       0  292.58    .045       0   306.6     .12       0
  354.19     .06       0  543.52     .12       0  581.79     .06       0
#XS Ineff= 2 , 0
          123.01  379.12  433.44          379.07
Permanent Ineff=
       F       F
Bank Sta=292.58,306.6
XS Rating Curve= 0 ,0
Exp/Cntr=0.3,0.1

Type RM Length L Ch R = 1 ,769.7   ,62.4,54.3,54.3
XS GIS Cut Line= 4
     2412038.281      332958.809     2412156.336      332988.323
     2412288.281      333443.184     2412491.406      333536.934
#Sta/Elev= 30
       0  375.52    35.3  375.77   50.43376.3529    74.6  376.61   95.77375.7201
   149.6   376.3   221.2  375.74  345.11375.5334   392.3   374.9   432.1  375.15
   436.1  374.88  446.47371.1954   447.9  370.71     452   370.3   462.9  370.73
     464  370.82   471.9  374.61   475.9   376.1   479.9  376.83   499.8  376.92
   511.7  377.48   547.5  381.28   587.3  386.49   651.2  393.54   671.2   396.2
   711.2  402.06   763.1  411.25   779.1  413.67     799     416     819  416.88
#Mann= 7 ,-1 , 0
       0     .12       0   50.43    .016       0   95.77     .06       0
  345.11     .12       0  446.47    .016       0   447.9    .045       0
   462.9     .06       0
#XS Ineff= 2 , 0
           69.14  377.52  482.97          377.52
Permanent Ineff=
       F       F
Bank Sta=447.9,462.9
XS Rating Curve= 0 ,0
Exp/Cntr=0.3,0.1

Type RM Length L Ch R = 1 ,715.4   ,427.5,400.4,370.9
XS GIS Cut Line= 4
       2412029.6      332974.434     2412102.517      332995.267
     2412234.461      333450.128     2412480.989      333566.448
#Sta/Elev= 30
       0  376.22      16  377.13    31.9   375.5   67.36376.2714   135.5  375.34
  284.01375.6407   358.4  374.69   378.3  376.35   402.2  372.85   414.1  372.03
  420.02 370.698     430  369.84  434.78 370.739     442  374.48     446  375.16
  474.85375.3416   481.8  375.19   517.6  376.98   529.6  378.58   561.3  379.86
   565.2  380.79  566.47381.8314   569.2  384.07   573.2  386.23  599.37389.2206
   679.8  397.86   715.4  403.28   782.5     415   802.3   417.7     822  419.33
#Mann= 8 ,-1 , 0
       0     .12       0   67.36    .016       0  284.01     .12       0
  420.02    .045       0  434.78     .12       0  474.85    .016       0
  566.47     .12       0  599.37     .06       0
#XS Ineff= 2 , 0
           11.35  377.74
Permanent Ineff=
       F       F
Bank Sta=420.02,434.78
XS Rating Curve= 0 ,0
Exp/Cntr=0.3,0.1

Type RM Length L Ch R = 1 ,315.1   ,207.5,222.4,237.3
XS GIS Cut Line= 3
     2411888.975      333437.976     2411975.781      333611.587
     2412406.336      333712.281
#Sta/Elev= 30
       0  373.49  207.36373.3036   253.9  373.38   257.8  373.07   265.8  370.04
  272.24368.2327   277.8  367.04   281.7  367.02  288.05368.1446   289.7  368.65
   293.7  371.17   297.7  372.68   301.7  373.35   313.6  374.15   337.5  373.38
   361.4   373.5   389.3  374.89   397.3   376.6   413.2   381.8   417.2  382.25
  425.79 382.041   433.1  381.36   437.1  381.62   441.1  384.76   445.1  387.14
  448.87 387.807   476.9  389.98   528.7  396.98   616.4  412.99   636.3  416.23
#Mann= 6 ,-1 , 0
       0     .06       0  207.36     .12       0  272.24    .045       0
  288.05     .12       0  425.79    .016       0  448.87     .06       0
#XS Ineff= 2 , 0
          156.04  376.11
Permanent Ineff=
       F       F
Bank Sta=272.24,288.05
XS Rating Curve= 0 ,0
Exp/Cntr=0.3,0.1

Type RM Length L Ch R = 1 ,92.7    ,91.7,92.7,93.7
XS GIS Cut Line= 3
     2411805.642      333557.767     2412085.156      333872.003
      2412333.42       333976.17
#Sta/Elev= 30
       0  375.27   142.8  374.72  257.82372.9626   289.6  371.24   293.6  370.49
   301.5   366.8   305.5  366.48   317.4  366.84   345.2  372.61   380.9  373.02
   412.6  371.52   428.5  372.79   436.4  375.65   452.2  387.46   456.2   389.4
   464.1     391     476  390.32   487.9  385.38   495.8  383.28   499.8   382.6
   511.6  382.95   527.5   379.9     575  392.42   590.8  394.81  607.22395.8642
   626.4  393.56   650.2  394.23     674  393.87  686.07391.2618   689.8  390.32
#Mann= 6 ,-1 , 0
       0     .06       0  257.82     .12       0   301.5    .045       0
   317.4     .12       0  607.22    .016       0  686.07     .12       0
#XS Ineff= 2 , 0
          266.56  374.46   345.3           374.7
Permanent Ineff=
       F       F
Bank Sta=301.5,317.4
XS Rating Curve= 0 ,0
Exp/Cntr=0.3,0.1
LCMann Table=0

Chan Stop Cuts=-1
Use User Specified Reach Order=0
Composite Channel Slope=5